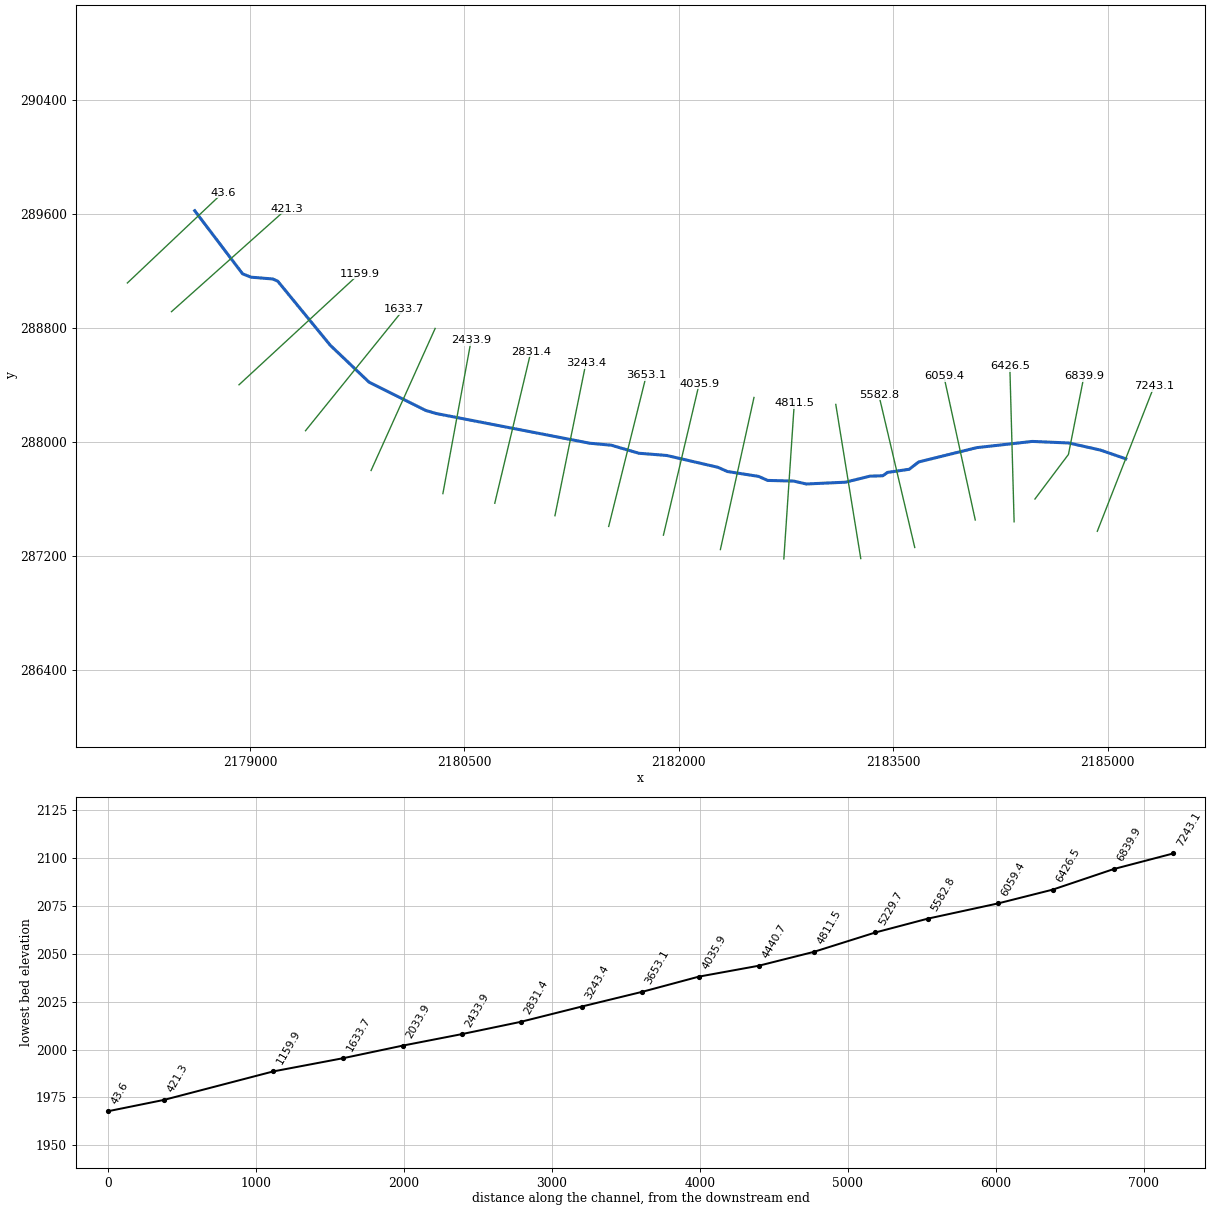
--- WadesCreek.prj (project) ---

Proj Title=WadesCreek
Current Plan=p01
Geom File=g01
Flow File=f01
Plan File=p01
DSS Export Rating Curves=0
DSS Export Rating Curve Sorted=0
DSS Export Volume Flow Curves=0
DXF OffsetX=0
DXF OffsetY=0
DXF ScaleX=0
DXF ScaleY=0

--- WadesCreek.p01 (plan) ---

Plan Title=Floodplain
Program Version=4.00
Geom File=g01
Flow File=f01
K Sum by GR=0
Std Step Tol=0.01
Critical Tol=0.01
Num of Std Step Trials=20
Max Error Tol=0.3
Flow Tol Ratio=0.001
Split Flow NTrial=30
Split Flow Tol=0.02
Split Flow Ratio=0.02
Log Output Level=0
Friction Slope Method=1
Unsteady Friction Slope Method=2
Unsteady Bridges Friction Slope Method=1
Global Log Level=0
CheckData=False
Run HTab=0
Run UNet=0
Run PostProcess=0
UNET Theta=0
UNET Theta Warmup=0
UNET ZTol=0
UNET ZSATol=0
UNET MxIter=0
UNET MaxInSteps=0
UNET DtIC=0
UNET DtMin=0
UNET MaxCRTS=0
UNET WFStab=0
UNET SFStab=0
UNET WFX=0
UNET SFX=0
UNET DSS MLevel=0
UNET DZMax Abort=0
UNET Convert EG Bridges=0
UNET Use Existing IB Tables=0
UNET Froude Limit=0
UNET Froude Power=0
Write IC File=0
Echo Input=False
Echo Output=False
Write Detailed=0

--- WadesCreek.f01 (steady flow) ---

Flow Title=NFF Regression Equation
Program Version=4.00
Number of Profiles=1
Profile Names=P100yr
River Rch & RM=WadesCreek,Main      ,7243.1
698.0248
River Rch & RM=WadesCreek,Main      ,6839.9
699.9431
River Rch & RM=WadesCreek,Main      ,6426.5
836.7404
River Rch & RM=WadesCreek,Main      ,5582.8
885.9012
River Rch & RM=WadesCreek,Main      ,1633.7
980.4929
River Rch & RM=WadesCreek,Main      ,43.6
1091.769
Boundary for River Rch & Prof#=WadesCreek,Main      ,1
Up Type=0
Dn Type= 1
Dn Known WS=1971.3

--- WadesCreek.g01 (geometry) ---

Geom Title=USGS 10m DEM
Program Version=4.10

River Reach=WadesCreek      ,Main
Reach XY= 30
     2185127.818      287883.992     2184951.255      287944.929
      2184729.38      287994.929      2184473.13      288005.867
     2184084.068      287962.117     2183679.381      287862.117
     2183612.193      287810.554      2183460.63      287788.679
     2183427.818      287765.242     2183337.193      287762.117
     2183165.318      287719.929     2182891.881      287707.429
      2182804.38      287727.742     2182621.568      287732.429
     2182559.068      287760.554     2182340.318      287794.929
      2182273.13      287824.617     2181915.318      287907.429
     2181720.006      287923.054     2181527.818      287979.304
     2181376.256      287993.367      2180304.38      288201.179
     2180229.381      288223.054     2179832.505      288421.492
     2179561.645      288679.997     2179194.267      289129.117
     2179159.068      289144.929     2179007.505      289157.429
     2178948.131      289180.867     2178613.113      289623.453

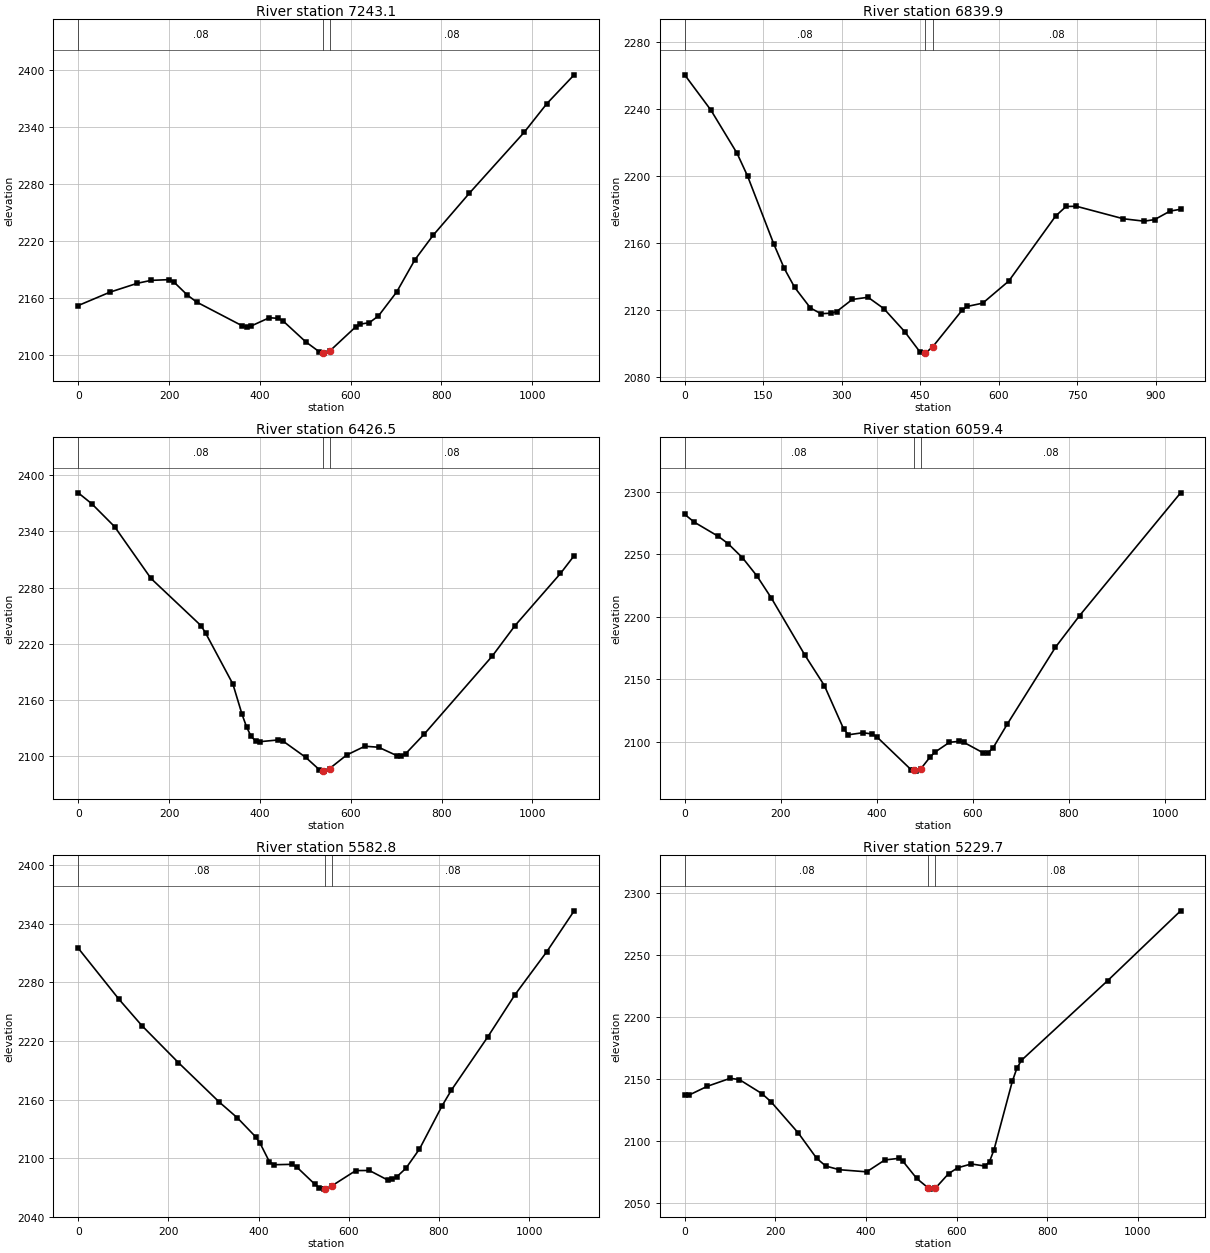
Type RM Length L Ch R = 1 ,7243.1  ,399.2,403.2,407.3
XS GIS Cut Line= 2
     2184928.409      287375.565     2185325.778      288392.868
#Sta/Elev= 30
       0 2152.48    70.1 2166.61   130.3 2175.93   160.3 2178.97   200.4 2179.75
   210.4  2177.4   240.5 2163.46   260.5 2156.26   360.7 2131.28   370.7 2129.97
   380.8 2130.96   420.8 2139.64   440.9 2139.01   450.9 2136.38     501 2114.33
     531 2103.79   538.6 2102.75   541.1 2102.41   553.6 2104.45   611.2 2130.12
   621.2  2132.9   641.3 2134.51   661.3 2141.59   701.4  2166.8   741.5  2200.7
   781.5 2226.36   861.7 2270.86   981.9 2334.66    1032 2364.94  1092.2 2395.29
#Mann= 3 , 0 , 0
       0     .08       0   538.6    .045       0   553.6     .08       0
Bank Sta=538.6,553.6
XS Rating Curve= 0 ,0
Exp/Cntr=0.3,0.1

Type RM Length L Ch R = 1 ,6839.9  ,408.2,413.4,418.4
XS GIS Cut Line= 3
     2184492.219      287602.233     2184726.557      287914.685
     2184834.713      288461.475
#Sta/Elev= 30
       0 2260.26    50.1 2239.22   100.1 2213.47   120.2 2199.88   170.2 2159.45
   190.3 2144.81   210.3 2133.43   240.4 2121.18   260.4 2117.77   280.4 2118.08
   290.4 2119.04   320.5 2126.29   350.5 2127.56   380.6 2120.83   420.4 2107.12
   450.3 2094.73   460.2 2094.25  474.04 2097.99   529.9 2119.69   539.9  2122.1
   569.7 2124.06   619.5 2137.24   709.1 2176.04     729 2181.73   748.9 2181.84
   838.5  2174.4   878.3 2172.96   898.2  2173.9     928    2179     948 2180.06
#Mann= 3 , 0 , 0
       0     .08       0   460.2    .045       0  474.04     .08       0
Bank Sta=460.2,474.04
XS Rating Curve= 0 ,0
Exp/Cntr=0.3,0.1

Type RM Length L Ch R = 1 ,6426.5  ,362.7,367.1,371.1
XS GIS Cut Line= 2
     2184346.462       287442.38     2184316.337      288534.064
#Sta/Elev= 30
       0 2381.37    30.1 2369.57    80.2  2345.1   160.3  2289.7   270.5 2239.14
   280.5 2231.29   340.6 2176.72   360.7 2144.36   370.7 2130.83   380.7 2120.68
   390.8 2115.69   400.8 2115.03   440.8 2116.87   450.9 2115.68     501 2098.23
     531 2084.99   538.5 2083.86     541 2083.48   553.5 2086.21   591.1  2100.7
   631.2 2110.11   661.3 2109.08   701.4 2100.12   711.4 2099.84   721.4 2102.31
   761.5 2122.86   911.8 2206.64   961.8  2239.2    1062 2295.07  1092.1 2314.11
#Mann= 3 , 0 , 0
       0     .08       0   538.5    .045       0   553.5     .08       0
Bank Sta=538.5,553.5
XS Rating Curve= 0 ,0
Exp/Cntr=0.3,0.1

Type RM Length L Ch R = 1 ,6059.4  ,476.2,476.6,477
XS GIS Cut Line= 2
     2184074.615      287455.021     2183854.935      288463.719
#Sta/Elev= 30
       0 2281.93      20 2275.67    70.2 2264.26    90.2 2258.53   120.3 2247.18
   150.3 2232.66   180.4 2214.92   250.6 2168.98   290.7 2144.88   330.8 2110.15
   340.8 2105.43   370.8 2107.08   390.9 2106.04   400.9 2103.43   471.1 2077.53
   476.5 2076.88   481.1 2076.33   491.5 2078.18   511.2  2087.8   521.2 2091.59
   551.2 2099.42   571.3 2100.17   581.3 2099.33   621.4 2090.94   631.4 2091.09
   641.5 2094.68   671.5 2113.98   771.8 2175.52   821.9  2200.8  1032.3 2299.16
#Mann= 3 , 0 , 0
       0     .08       0   476.5    .045       0   491.5     .08       0
Bank Sta=476.5,491.5
XS Rating Curve= 0 ,0
Exp/Cntr=0.3,0.1

Type RM Length L Ch R = 1 ,5582.8  ,354.7,353.1,351.5
XS GIS Cut Line= 2
     2183651.135      287262.224     2183399.661      288332.693
#Sta/Elev= 30
       0 2314.85    90.8 2262.34   141.2  2235.6   221.9 2197.88   312.7 2157.43
   353.1 2141.18   393.4 2121.84   403.5 2115.03   423.7 2096.54   433.8 2093.29
   474.1 2093.71   484.2 2091.09   524.6 2073.37   534.7 2069.75   544.8 2068.34
   547.1  2068.6   562.1  2071.6   615.4 2087.31   645.6 2087.41     686  2077.7
   696.1 2078.24   706.2  2080.9   726.4 2089.59   756.6  2109.3     807 2153.74
   827.2 2169.49   907.9 2223.95   968.5 2267.29  1039.1 2311.35  1099.6 2353.05
#Mann= 3 , 0 , 0
       0     .08       0   547.1    .045       0   562.1     .08       0
Bank Sta=547.1,562.1
XS Rating Curve= 0 ,0
Exp/Cntr=0.3,0.1

Type RM Length L Ch R = 1 ,5229.7  ,423.2,418.1,413
XS GIS Cut Line= 2
     2183273.438      287184.691     2183098.647      288265.155
#Sta/Elev= 30
       0 2137.04      10 2136.97    50.2 2144.01   100.4 2150.39   120.5 2149.42
   170.7 2138.01   190.8 2131.41     251 2106.24   291.2    2086   311.3 2079.74
   341.4 2076.78   401.7 2075.07   441.8 2084.65     472  2085.9     482 2083.43
   512.1 2069.74     538 2061.93   542.2 2061.14     553 2061.75   582.4  2073.6
   602.5 2078.33   632.6 2081.42   662.7  2079.7   672.8 2083.32   682.8 2093.02
     723 2147.88     733 2158.38   743.1 2164.86   933.8 2229.18  1094.5 2285.31
#Mann= 3 , 0 , 0
       0     .08       0     538    .045       0     553     .08       0
Bank Sta=538,553
XS Rating Curve= 0 ,0
Exp/Cntr=0.3,0.1

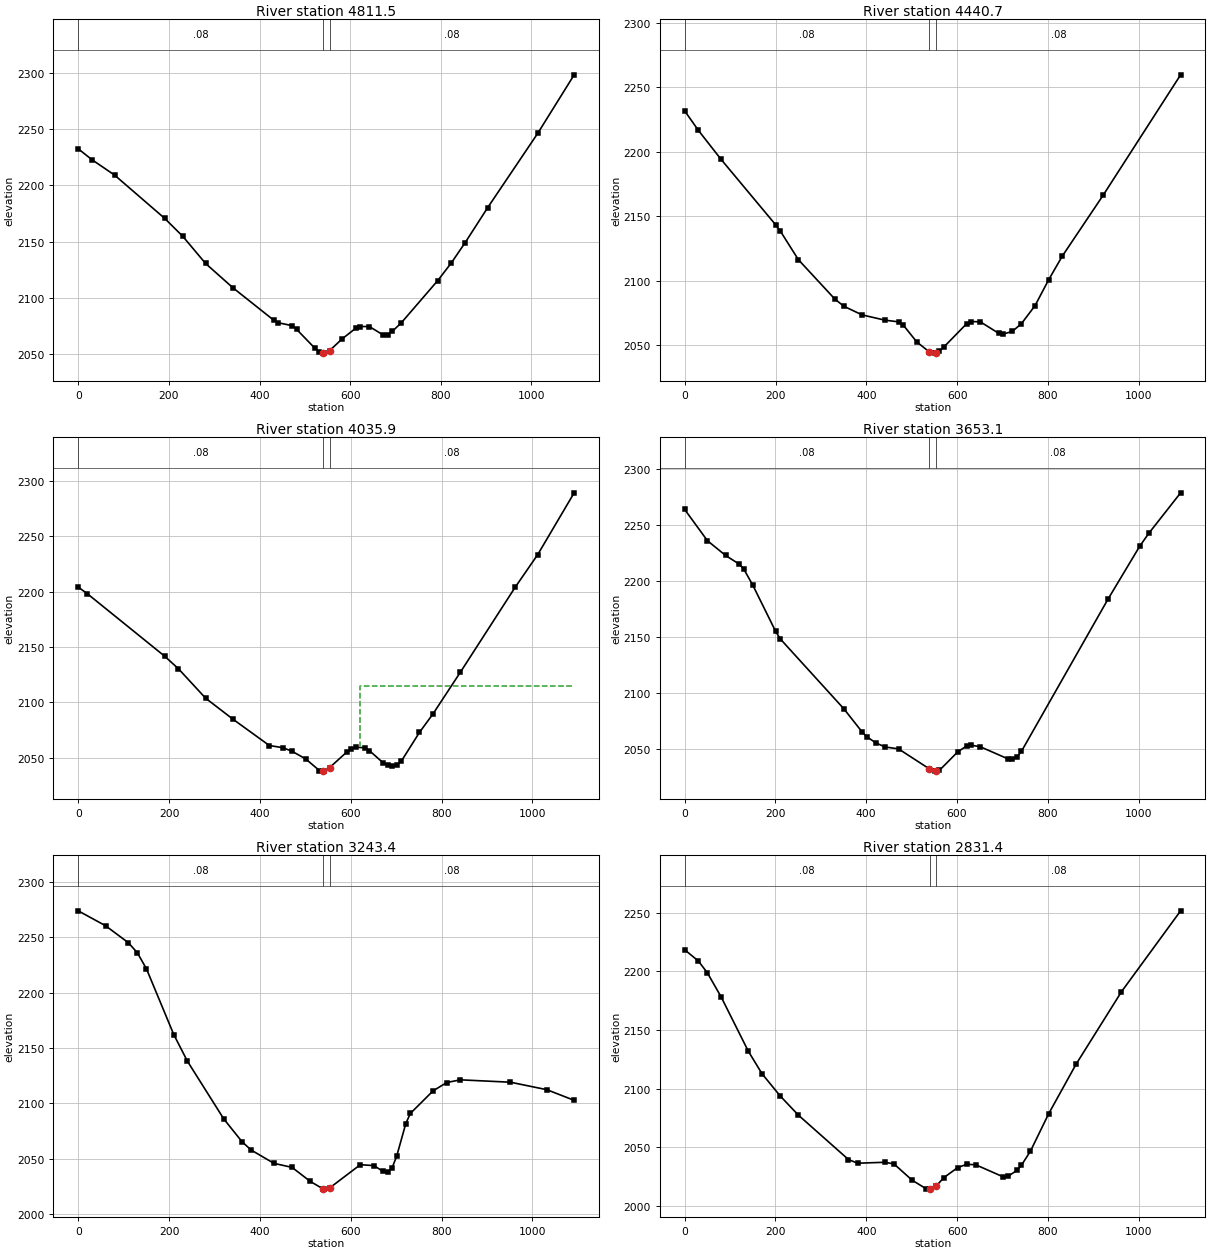
Type RM Length L Ch R = 1 ,4811.5  ,374.2,370.8,367.4
XS GIS Cut Line= 2
     2182735.128      287181.917     2182808.357      288273.566
#Sta/Elev= 30
       0 2232.38    30.1 2222.76    80.3    2209   190.7 2170.62   230.9 2154.57
     281 2130.56   341.3 2108.99   431.6 2080.13   441.7 2077.91   471.8 2075.37
   481.8 2072.08     522 2055.36     532 2052.15   539.6 2051.25     542 2050.97
   554.6  2053.2   582.2  2063.6   612.3  2073.1   622.3  2074.6   642.4 2074.56
   672.5 2067.15   682.6 2067.45   692.6  2070.2   712.7 2077.84     793  2115.3
   823.1 2131.05   853.2  2148.8   903.4 2180.18  1013.8 2246.14  1094.1 2298.04
#Mann= 3 , 0 , 0
       0     .08       0   539.6    .045       0   554.6     .08       0
Bank Sta=539.6,554.6
XS Rating Curve= 0 ,0
Exp/Cntr=0.3,0.1

Type RM Length L Ch R = 1 ,4440.7  ,405,404.8,404.4
XS GIS Cut Line= 2
     2182291.182      287247.543     2182526.264      288314.027
#Sta/Elev= 30
       0  2231.8    30.1 2216.68    80.2 2194.12   200.4 2143.33   210.4 2138.63
   250.5 2116.24   330.6 2085.75   350.7  2080.1   390.8 2073.42   440.8 2069.36
   470.9 2068.04   480.9 2065.73     511 2052.48   538.5 2044.77     551 2043.76
   553.5 2044.16   561.1 2045.36   571.1 2048.62   621.2 2066.71   631.2 2068.29
   651.2 2068.03   691.3  2059.2   701.3 2058.52   721.4 2060.63   741.4 2066.55
   771.5 2080.61   801.5  2100.7   831.6  2119.1   921.8 2166.47  1092.1 2259.77
#Mann= 3 , 0 , 0
       0     .08       0   538.5    .045       0   553.5     .08       0
Bank Sta=538.5,553.5
XS Rating Curve= 0 ,0
Exp/Cntr=0.3,0.1

Type RM Length L Ch R = 1 ,4035.9  ,383,382.8,382.5
XS GIS Cut Line= 2
     2181892.604      287348.589     2182143.202      288411.454
#Sta/Elev= 30
       0 2204.08      20 2198.16   190.4 2141.73   220.4 2130.54   280.5 2103.88
   340.6 2084.95   420.8 2061.19   450.8 2059.18   470.9 2055.96   500.9 2049.08
     531 2038.61   538.5  2038.2     541 2038.07   553.5 2041.22   591.1 2055.21
   601.1 2058.19   611.1 2059.66   631.2  2059.1   641.2 2056.55   671.2 2045.64
   681.2 2043.16   691.3 2042.52   701.3 2043.73   711.3 2046.95   751.4 2073.01
   781.4 2089.83   841.6 2127.38   961.8 2203.75  1011.9 2233.49    1092 2289.15
#Mann= 3 , 0 , 0
       0     .08       0   538.5    .045       0   553.5     .08       0
#XS Ineff= 2 , 0
                           619.8         2114.93
Permanent Ineff=
       F       F
Bank Sta=538.5,553.5
XS Rating Curve= 0 ,0
Exp/Cntr=0.3,0.1

Type RM Length L Ch R = 1 ,3653.1  ,408.7,409.7,410.7
XS GIS Cut Line= 2
     2181509.632      287409.744     2181773.046      288470.197
#Sta/Elev= 30
       0 2263.65    50.1  2235.8    90.2 2222.58   120.3 2214.87   130.3 2210.42
   150.4 2195.85   200.5 2154.78   210.5  2148.2   350.9 2085.68     391 2065.07
     401  2060.9     421  2055.4   441.1 2051.74   471.2 2049.99   538.5 2032.31
   551.4 2030.14   553.5  2030.3   561.4 2030.89   601.5 2047.27   621.5  2052.7
   631.6 2053.27   651.6 2051.84   711.7 2041.19   721.8 2040.81   731.8 2042.66
   741.8 2047.67   932.3 2183.35  1002.5 2230.79  1022.5 2242.34  1092.7 2278.51
#Mann= 3 , 0 , 0
       0     .08       0   538.5    .045       0   553.5     .08       0
Bank Sta=538.5,553.5
XS Rating Curve= 0 ,0
Exp/Cntr=0.3,0.1

Type RM Length L Ch R = 1 ,3243.4  ,412.8,412,411.2
XS GIS Cut Line= 2
     2181133.576      287484.779     2181350.185       288555.08
#Sta/Elev= 30
       0 2273.88    60.1 2260.44   110.2 2245.14   130.2 2235.99   150.3 2221.44
   210.4 2162.09   240.4 2138.04   320.6  2085.8   360.7 2065.27   380.7 2057.78
   430.8 2045.75   470.9 2042.06   510.9 2029.43   538.5 2022.78     541 2022.43
   553.5 2023.46   621.1 2044.48   651.2  2043.7   671.2 2038.41   681.2 2037.67
   691.3 2041.79   701.3 2052.28   721.3 2081.68   731.3 2090.81   781.4 2111.22
   811.5 2118.76   841.5 2121.18   951.7 2119.03  1031.9 2112.27    1092 2102.66
#Mann= 3 , 0 , 0
       0     .08       0   538.5    .045       0   553.5     .08       0
Bank Sta=538.5,553.5
XS Rating Curve= 0 ,0
Exp/Cntr=0.3,0.1

Type RM Length L Ch R = 1 ,2831.4  ,396.4,397.5,398.7
XS GIS Cut Line= 2
     2180712.545      287572.534     2180965.413      288635.263
#Sta/Elev= 30
       0 2218.33    30.1 2208.79    50.1 2198.62    80.2 2178.24   140.3 2131.84
   170.4 2112.71   210.5 2093.77   250.6 2077.43   360.8 2039.65   380.8 2036.52
     441 2037.33     461 2035.92   501.1 2022.03   531.2 2014.91   539.3 2014.54
   541.2 2014.45   554.3 2017.25   571.2 2024.35   601.3 2032.77   621.4 2035.64
   641.4 2035.15   701.5 2024.91   711.6 2025.22   731.6 2030.34   741.6  2034.7
   761.7 2046.85   801.8  2078.7   861.9 2120.71   962.1 2182.59  1092.4 2251.51
#Mann= 3 , 0 , 0
       0     .08       0   539.3    .045       0   554.3     .08       0
Bank Sta=539.3,554.3
XS Rating Curve= 0 ,0
Exp/Cntr=0.3,0.1

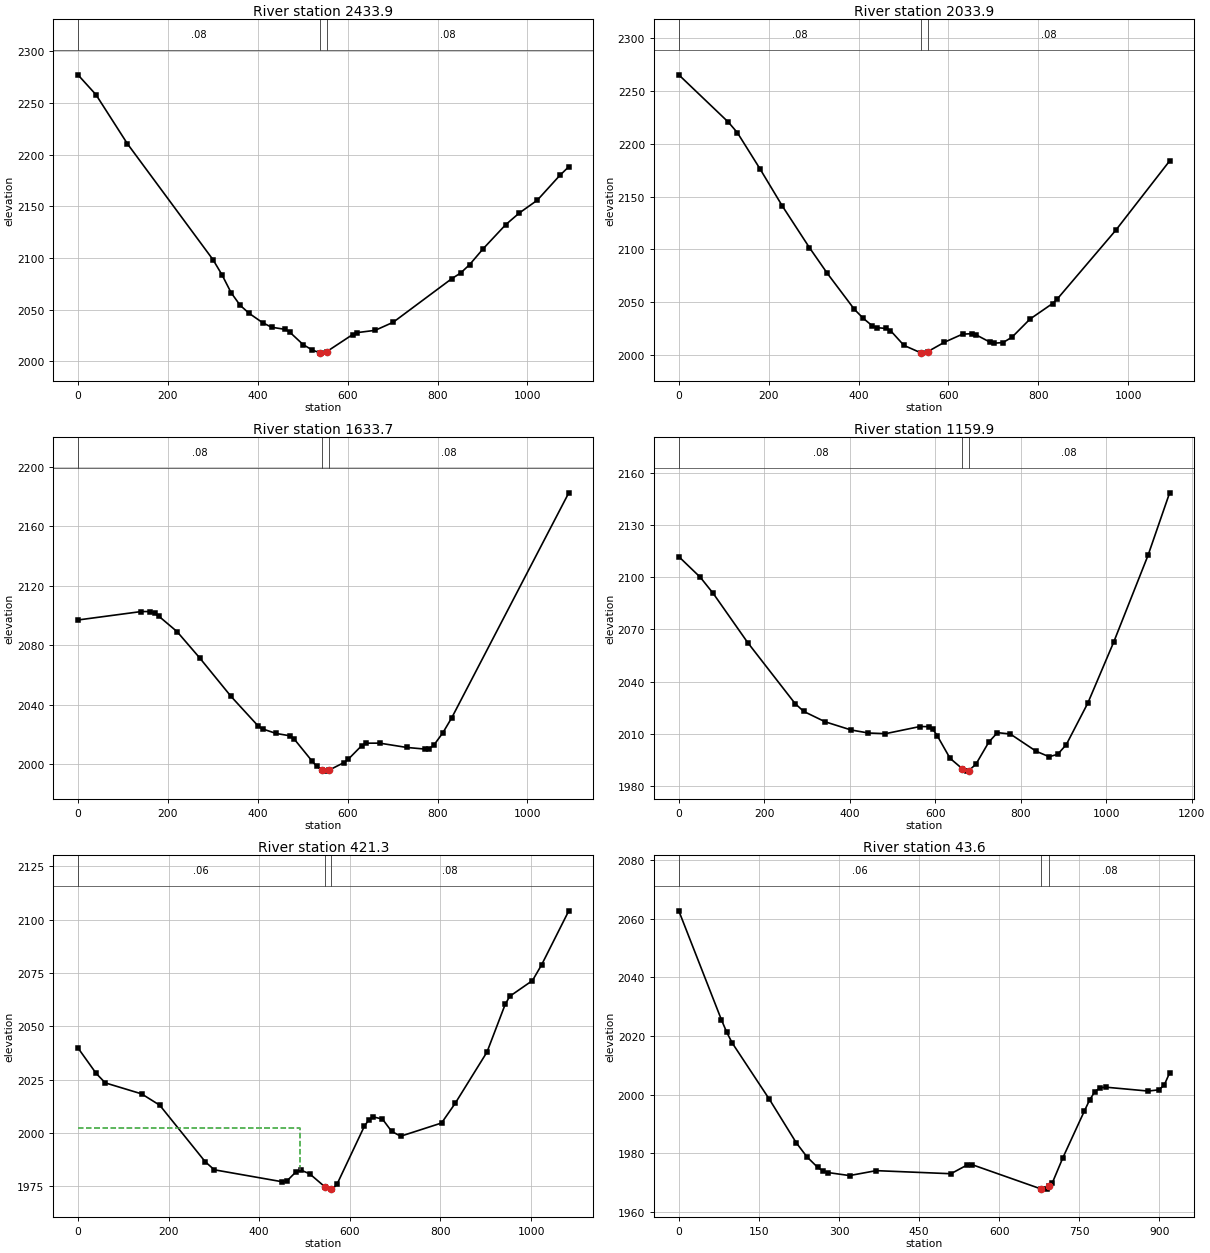
Type RM Length L Ch R = 1 ,2433.9  ,405.4,400,394.5
XS GIS Cut Line= 2
     2180349.561      287639.944     2180546.947      288713.957
#Sta/Elev= 30
       0  2277.2    40.1 2257.98   110.2 2210.42   300.6 2098.33   320.6 2083.69
   340.6  2066.6   360.7 2054.37   380.7 2046.58   410.8  2037.5   430.8 2033.08
   460.8 2031.06   470.9 2028.48   500.9 2016.33     521 2011.11   538.5 2008.29
     541 2008.05   553.5  2009.5   611.1 2026.01   621.1 2027.88   661.2  2030.1
   701.3 2037.89   831.5 2080.01   851.6  2085.6   871.6 2093.76   901.6 2109.04
   951.7  2132.3   981.8 2143.53  1021.9 2155.92    1072  2179.9    1092 2188.32
#Mann= 3 , 0 , 0
       0     .08       0   538.5    .045       0   553.5     .08       0
Bank Sta=538.5,553.5
XS Rating Curve= 0 ,0
Exp/Cntr=0.3,0.1

Type RM Length L Ch R = 1 ,2033.9  ,405.8,400.1,394.3
XS GIS Cut Line= 2
     2179847.146      287802.027     2180295.263      288797.846
#Sta/Elev= 30
       0 2265.07   110.2 2220.38   130.2 2210.46   180.3 2176.44   230.4 2141.03
   290.5 2101.83   330.6 2077.32   390.7 2043.38   410.8 2034.78   430.8 2027.73
   440.8 2026.12   460.8 2025.38   470.9 2023.37   500.9 2009.35   538.5 2002.34
     541 2002.04   553.5 2003.36   591.1 2012.37   631.2 2019.98   651.2 2020.39
   661.2 2019.37   691.3 2012.64   701.3 2011.42   721.3 2012.02   741.4 2017.14
   781.4 2034.24   831.5 2048.92   841.5 2052.95   971.8 2117.98    1092  2183.7
#Mann= 3 , 0 , 0
       0     .08       0   538.5    .045       0   553.5     .08       0
Bank Sta=538.5,553.5
XS Rating Curve= 0 ,0
Exp/Cntr=0.3,0.1

Type RM Length L Ch R = 1 ,1633.7  ,477.1,473.8,470.5
XS GIS Cut Line= 2
     2179388.396       288081.04     2180073.901      288931.068
#Sta/Elev= 30
       0 2097.08   140.3 2102.73   160.3 2102.76   170.3 2101.49   180.3 2099.51
   220.4 2089.29   270.5 2071.71   340.6 2045.71   400.7 2025.91   410.8 2023.86
   440.8 2020.83   470.9 2019.29   480.9 2017.14     521  2002.2     531 1998.82
   542.5 1996.09     551 1995.51   557.5 1996.01   591.1 2001.14   601.1 2003.41
   631.2 2012.61   641.2 2014.28   671.2 2014.32   731.3 2011.43   771.4 2010.34
   781.4  2010.7   791.4 2012.82   811.5 2021.12   831.5  2031.3    1092 2182.53
#Mann= 3 , 0 , 0
       0     .08       0   542.5    .045       0   557.5     .08       0
Bank Sta=542.5,557.5
XS Rating Curve= 0 ,0
Exp/Cntr=0.3,0.1

Type RM Length L Ch R = 1 ,1159.9  ,738.9,738.6,738.1
XS GIS Cut Line= 2
     2178923.122      288403.151      2179765.93      289183.097
#Sta/Elev= 30
       0 2111.75    50.4 2099.86    80.6 2090.59   161.2 2062.39     272 2027.39
   292.1 2022.89   342.5 2016.89   402.9 2012.22   443.2 2010.48   483.5 2010.08
   564.1 2014.19   584.2 2014.12   594.3 2012.61   604.4 2009.02   634.6 1995.94
   663.5  1989.9   674.9 1988.58   678.5 1988.91     695 1992.51   725.3 2005.25
   745.4 2010.69   775.6 2009.89   836.1 1999.98   866.3 1996.86   886.4 1998.22
   906.6 2003.82   956.9 2027.65  1017.4 2062.63    1098 2112.63  1148.3 2148.38
#Mann= 3 , 0 , 0
       0     .08       0   663.5    .045       0   678.5     .08       0
Bank Sta=663.5,678.5
XS Rating Curve= 0 ,0
Exp/Cntr=0.3,0.1

Type RM Length L Ch R = 1 ,421.3   ,377,377.7,378.3
XS GIS Cut Line= 2
     2178450.496      288915.637      2179257.75      289637.972
#Sta/Elev= 30
       0 2039.89    40.1 2027.97    60.2 2023.51   140.4 2018.36   180.5 2013.04
   280.8 1986.56   300.9 1982.77   451.4 1977.14   461.4 1977.59   481.4 1981.86
   491.5 1982.67   511.5 1980.87   544.2 1974.92   559.2 1973.72   561.7 1973.71
   571.7    1976   631.9 2003.11   641.9 2006.21     652 2007.54     672 2006.54
   692.1 2000.82   712.1  1998.5   802.4  2004.7   832.5 2013.92   902.7 2037.95
   942.8 2060.28   952.9 2064.08    1003 2071.45  1023.1 2078.78  1083.2 2104.14
#Mann= 3 , 0 , 0
       0     .06       0   544.2    .045       0   559.2     .08       0
#XS Ineff= 2 , 0
          490.28  2002.3
Permanent Ineff=
       F       F
Bank Sta=544.2,559.2
XS Rating Curve= 0 ,0
Exp/Cntr=0.3,0.1

Type RM Length L Ch R = 1 ,43.6    ,45.9,43.6,41.4
XS GIS Cut Line= 2
     2178141.877      289116.917     2178808.954      289749.312
#Sta/Elev= 30
       0 2062.65    79.9 2025.48    89.9 2021.22    99.9 2017.65   169.8 1998.37
   219.8 1983.65   239.8 1978.84   259.8 1975.26   269.8 1974.01   279.8 1973.44
   319.7 1972.42   369.7  1974.1   509.6 1973.05   539.5 1975.98   549.5 1976.12
   678.6 1967.85   679.4  1967.8   689.4 1967.83   693.6  1968.7   699.4 1969.89
   719.4 1978.55   759.3 1994.33   769.3 1998.17   779.3 2001.07   789.3 2002.35
   799.3 2002.55   879.2 2001.22   899.2 2001.65   909.2 2003.32   919.2 2007.42
#Mann= 3 , 0 , 0
       0     .06       0   678.6    .045       0   693.6     .08       0
Bank Sta=678.6,693.6
XS Rating Curve= 0 ,0
Exp/Cntr=0.3,0.1

Chan Stop Cuts=-1
Use User Specified Reach Order=0
Composite Channel Slope=5